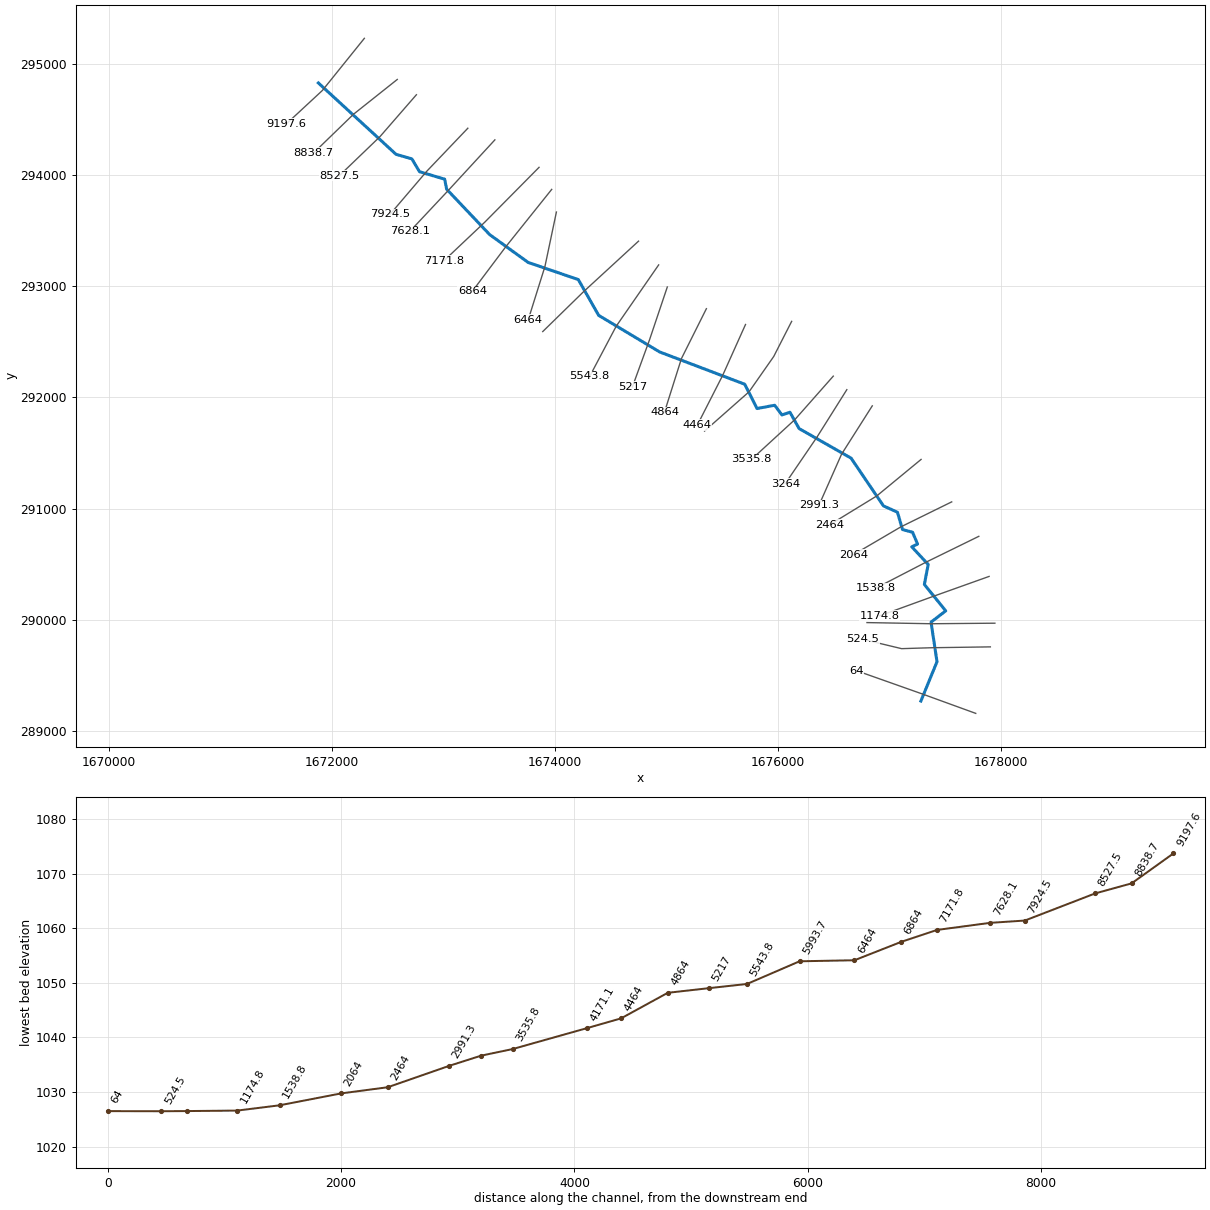
--- ChrycpRn.prj (project) ---

Proj Title=ChrycpRn
Current Plan=p01
Geom File=g01
Flow File=f01
Plan File=p01
DSS Export Rating Curves=0
DSS Export Rating Curve Sorted=0
DSS Export Volume Flow Curves=0
DXF OffsetX=0
DXF OffsetY=0
DXF ScaleX=0
DXF ScaleY=0

--- ChrycpRn.p01 (plan) ---

Plan Title=Floodplain
Program Version=4.00
Geom File=g01
Flow File=f01
K Sum by GR=0
Std Step Tol=0.01
Critical Tol=0.01
Num of Std Step Trials=20
Max Error Tol=0.3
Flow Tol Ratio=0.001
Split Flow NTrial=30
Split Flow Tol=0.02
Split Flow Ratio=0.02
Log Output Level=0
Friction Slope Method=1
Unsteady Friction Slope Method=2
Unsteady Bridges Friction Slope Method=1
Global Log Level=0
CheckData=False
Run HTab=0
Run UNet=0
Run PostProcess=0
UNET Theta=0
UNET Theta Warmup=0
UNET ZTol=0
UNET ZSATol=0
UNET MxIter=0
UNET MaxInSteps=0
UNET DtIC=0
UNET DtMin=0
UNET MaxCRTS=0
UNET WFStab=0
UNET SFStab=0
UNET WFX=0
UNET SFX=0
UNET DSS MLevel=0
UNET DZMax Abort=0
UNET Convert EG Bridges=0
UNET Use Existing IB Tables=0
UNET Froude Limit=0
UNET Froude Power=0
Write IC File=0
Echo Input=False
Echo Output=False
Write Detailed=0

--- ChrycpRn.f01 (steady flow) ---

Flow Title=NFF Regression Equation
Program Version=4.00
Number of Profiles=1
Profile Names=P100yr
River Rch & RM=ChrycpRn,Main      ,9197.6
768.1730
River Rch & RM=ChrycpRn,Main      ,7924.5
784.4978
River Rch & RM=ChrycpRn,Main      ,7171.8
866.6811
River Rch & RM=ChrycpRn,Main      ,4171.1
943.8470
River Rch & RM=ChrycpRn,Main      ,3535.8
1140.782
River Rch & RM=ChrycpRn,Main      ,64
1211.450
Boundary for River Rch & Prof#=ChrycpRn,Main      ,1
Up Type=0
Dn Type=3
Dn Slope=0.003863

--- ChrycpRn.g01 (geometry) ---

Geom Title=USGS 3m DEM
Program Version=4.00

River Reach=ChrycpRn     ,Main
Reach XY= 30
     1671880.987      294825.810     1672577.424      294184.516
     1672719.553      294143.457     1672787.686      294028.401
     1673013.283      293961.169     1673031.382      293870.893
     1673416.998      293463.015     1673762.255      293212.887
     1674211.707      293058.921     1674394.441      292737.254
     1674941.095      292408.592     1675704.441      292118.287
     1675814.338      291900.036     1675972.711      291929.590
     1676037.509      291842.757     1676109.571      291866.604
     1676191.737      291719.898     1676657.519      291454.476
     1676947.821      291025.499     1677073.794      290967.954
     1677118.633      290812.694     1677209.093      290788.331
     1677253.935      290682.060     1677201.838      290657.696
     1677349.324      290498.806     1677314.848      290319.440
     1677506.402      290082.011     1677374.720      289980.664
     1677428.119      289625.040     1677283.746      289271.752

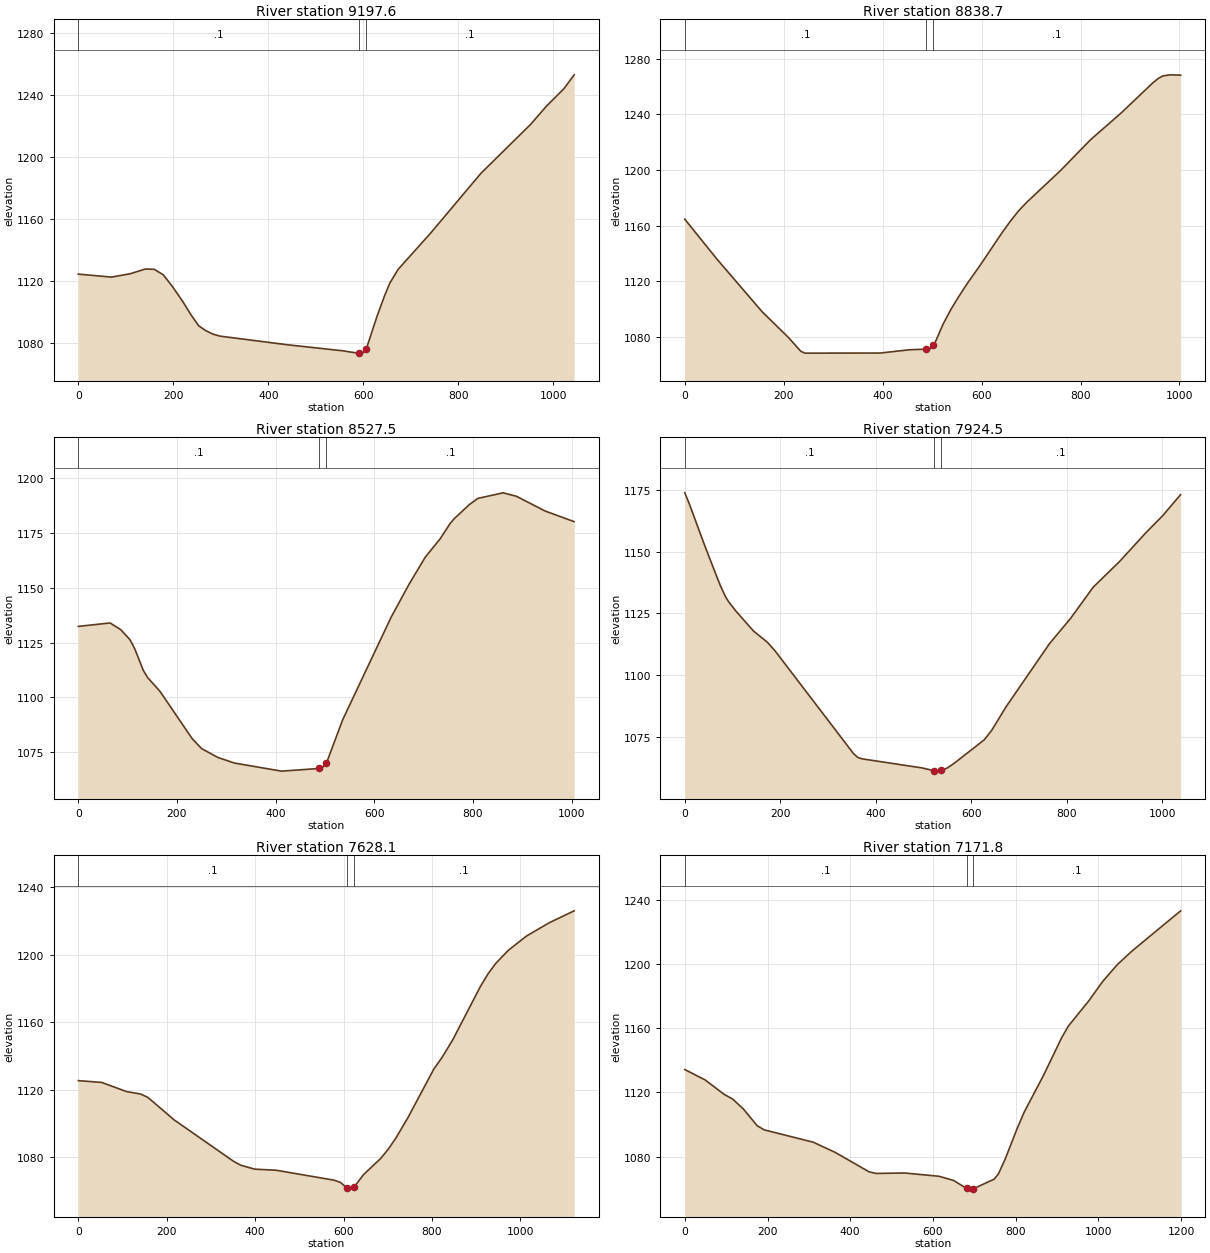
Type RM Length L Ch R = 1 ,9197.6,363.946,358.918,358.231
XS GIS Cut Line= 3
     1672293.347      295226.714     1671916.994      294758.311
     1671592.454      294456.844
#Sta/Elev= 30
       0 1124.61    69.9 1122.68   110.0 1124.91   140.9 1127.89   159.9 1127.71
   178.8 1124.18   197.8 1116.76   219.8 1106.99   237.5 1098.25   253.6 1091.25
   267.9 1088.26   283.1 1085.96   298.4 1084.64   439.3 1079.11   557.3 1075.17
   587.7 1073.69   590.1 1073.72   599.8 1074.02   605.1 1076.53   608.2 1078.24
   629.0 1097.59   645.2 1111.06   655.6 1118.73   673.1 1127.62   742.4 1151.31
   847.5 1189.56   952.2 1221.14   985.5 1232.87  1022.0 1244.02  1043.8 1253.05
#Mann= 3 , 0 , 0
       0     0.1       0   590.1   0.045       0   605.1     0.1       0
Bank Sta=   590.1,   605.1
Exp/Cntr=0.3,0.1

Type RM Length L Ch R = 1 ,8838.7,307.082,311.222,312.137
XS GIS Cut Line= 3
     1672588.446      294857.171     1672196.133      294544.707
     1671837.029      294195.730
#Sta/Elev= 30
       0 1164.61    65.1 1135.83   156.2 1098.05   209.2 1079.57   234.5 1069.54
   242.9 1068.21   247.2 1068.20   395.0 1068.26   454.2 1070.62   487.2 1071.06
   496.4 1071.34   502.2 1073.78   505.6 1075.48   522.2 1089.15   538.7 1100.13
   555.2 1109.69   571.8 1118.74   597.2 1131.52   640.3 1154.36   657.4 1162.83
   674.4 1170.48   691.4 1176.86   759.6 1199.66   820.2 1221.82   882.7 1241.28
   947.0 1263.06   958.2 1266.19   966.6 1267.78   981.1 1268.54  1002.3 1268.29
#Mann= 3 , 0 , 0
       0     0.1       0   487.2   0.045       0   502.2     0.1       0
Bank Sta=   487.2,   502.2
Exp/Cntr=0.3,0.1

Type RM Length L Ch R = 1 ,8527.5,605.806,603.031,593.098
XS GIS Cut Line= 3
     1672760.038      294719.900     1672432.583      294342.574
     1672068.411      293991.857
#Sta/Elev= 30
       0 1132.38    64.3 1133.95    85.9 1130.91   104.0 1126.49   108.5 1124.76
   114.8 1121.94   131.7 1112.34   140.2 1109.11   165.3 1102.83   230.8 1081.18
   250.0 1076.62   283.2 1072.57   316.8 1070.04   412.0 1066.37   488.1 1067.58
   493.6 1067.58   503.1 1070.08   535.9 1089.78   634.1 1136.55   669.9 1151.38
   703.5 1164.02   733.0 1172.17   753.9 1179.36   762.3 1181.56   792.7 1187.93
   809.8 1190.75   861.1 1193.30   888.2 1191.72   946.7 1184.97  1005.2 1180.16
#Mann= 3 , 0 , 0
       0     0.1       0   488.1   0.045       0   503.1     0.1       0
Bank Sta=   488.1,   503.1
Exp/Cntr=0.3,0.1

Type RM Length L Ch R = 1 ,7924.5,295.841,296.376,295.508
XS GIS Cut Line= 3
     1673221.195      294419.018     1672852.272      294031.565
     1672525.386      293647.524
#Sta/Elev= 30
       0 1173.68    10.1 1168.93    42.0 1152.26    68.4 1139.19    74.8 1136.13
    85.2 1131.80    91.2 1129.92   107.6 1125.86   144.0 1117.92   173.1 1113.38
   189.5 1109.83   353.5 1068.47   362.3 1066.94   371.6 1066.35   496.7 1062.71
     522 1061.59   530.3 1061.40     537 1061.71   549.5 1062.61   564.0 1064.50
   627.4 1074.02   643.0 1077.83   672.6 1087.20   764.2 1112.85   808.2 1122.99
   855.8 1135.63   910.7 1145.91   965.7 1157.50  1001.6 1164.52  1038.9 1172.96
#Mann= 3 , 0 , 0
       0     0.1       0     522   0.045       0     537     0.1       0
Bank Sta=     522,     537
Exp/Cntr=0.3,0.1

Type RM Length L Ch R = 1 ,7628.1,457.244,456.29,454.946
XS GIS Cut Line= 3
     1673463.727      294314.440     1673043.875      293857.655
     1672701.325      293491.917
#Sta/Elev= 30
       0 1125.30    52.8 1124.23   108.9 1118.81   140.6 1117.37   157.3 1115.36
   216.5 1102.07   350.8 1077.53   366.9 1075.20   399.2 1072.81   447.5 1072.18
   577.8 1066.32   592.7 1065.00   608.2 1061.54   614.3 1060.98   623.2 1061.98
   645.0 1069.57   683.8 1079.13   701.2 1084.72   718.5 1091.36   745.8 1103.49
   803.9 1132.07   822.7 1139.07   846.6 1149.36   909.6 1181.18   927.0 1188.70
   944.3 1194.83   972.6 1202.56  1013.8 1211.03  1065.9 1218.99  1121.5 1225.96
#Mann= 3 , 0 , 0
       0     0.1       0   608.2   0.045       0   623.2     0.1       0
Bank Sta=   608.2,   623.2
Exp/Cntr=0.3,0.1

Type RM Length L Ch R = 1 ,7171.8,305.42,307.784,311.432
XS GIS Cut Line= 3
     1673859.787      294067.459     1673372.548      293574.210
     1673005.374      293226.649
#Sta/Elev= 30
       0 1134.21    49.2 1127.73    95.0 1118.77   116.0 1115.77   141.4 1109.68
   175.2 1099.17   192.1 1096.61   310.4 1088.94   363.7 1082.57   445.5 1070.47
   462.4 1069.45   531.6 1069.73   614.5 1067.70   650.0 1065.09   681.2 1060.14
   691.1 1059.68   696.2 1059.73   747.8 1065.85   758.3 1069.16   775.1 1078.65
   803.9 1097.64   821.2 1107.93   867.5 1130.64   911.3 1154.08   927.6 1161.35
   976.7 1176.97  1011.2 1189.33  1045.7 1199.56  1080.3 1207.84  1198.9 1233.12
#Mann= 3 , 0 , 0
       0     0.1       0   681.2   0.045       0   696.2     0.1       0
Bank Sta=   681.2,   696.2
Exp/Cntr=0.3,0.1

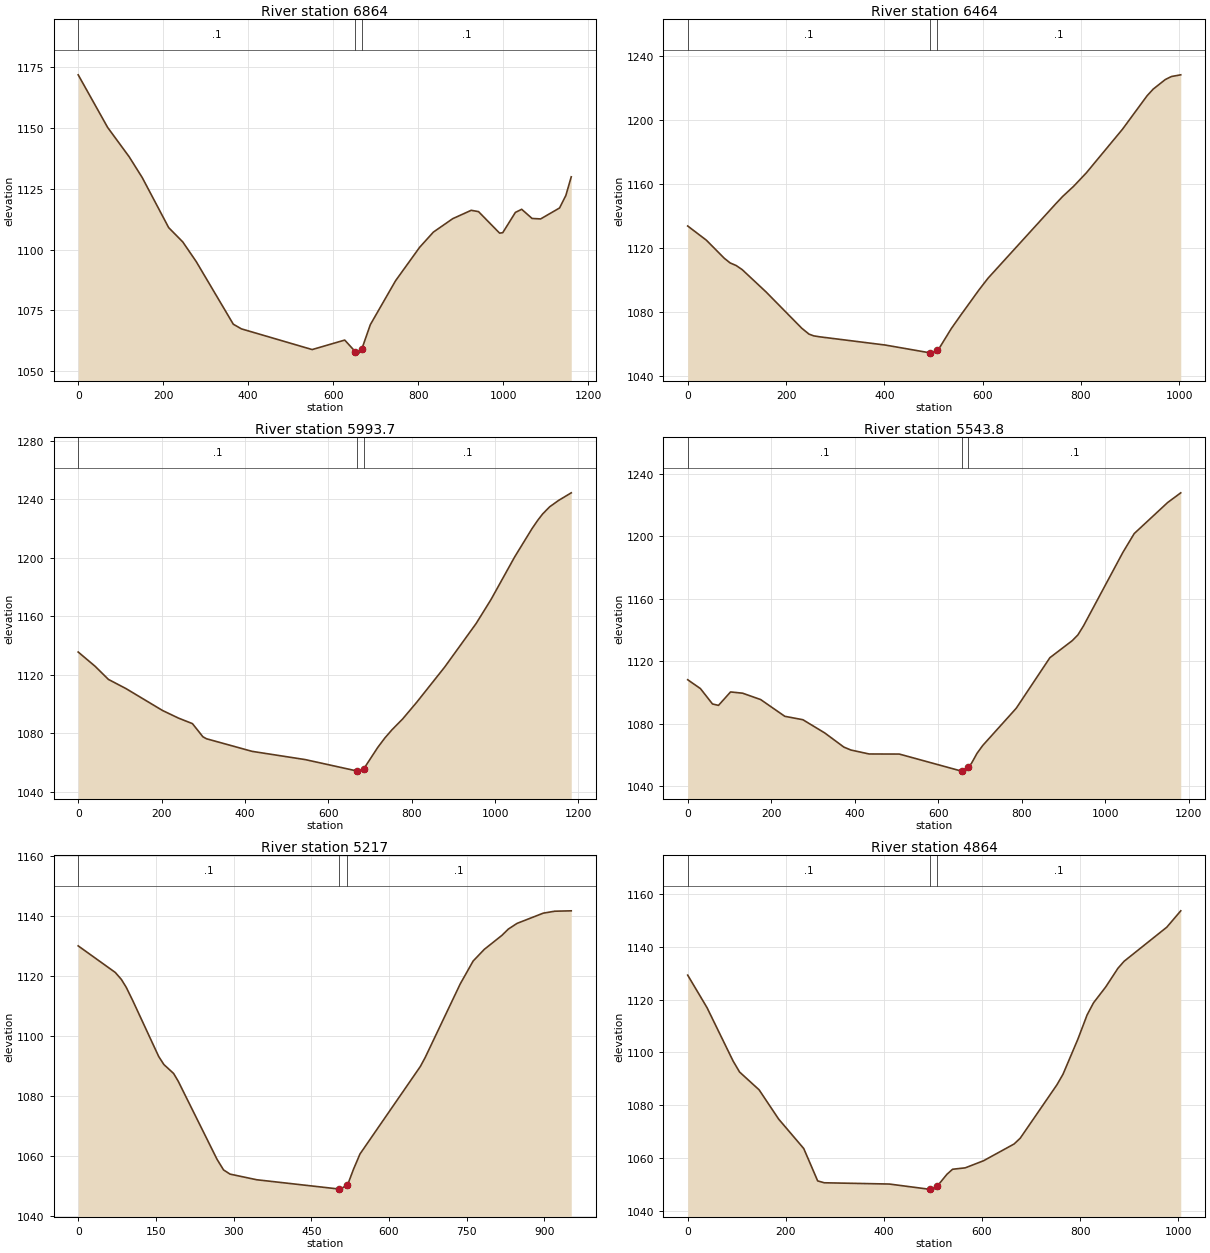
Type RM Length L Ch R = 1 ,6864,389.445,400,407.706
XS GIS Cut Line= 3
     1673973.265      293869.429     1673561.744      293354.067
     1673261.485      292953.764
#Sta/Elev= 30
       0 1171.80    69.3 1150.19   120.0 1138.12   150.9 1129.52   212.9 1109.03
   246.0 1103.17   277.6 1095.11   364.9 1069.37   383.9 1067.46   550.4 1058.95
   627.0 1062.85     652 1058.08   660.6 1057.49     667 1059.05   687.2 1069.16
   746.5 1087.19   803.3 1100.97   835.6 1107.20   881.1 1112.72   924.6 1116.15
   941.8 1115.61   991.4 1106.77   998.8 1106.97  1028.5 1115.29  1043.3 1116.57
  1067.7 1112.81  1087.9 1112.61  1132.4 1117.11  1147.2 1122.24  1159.9 1129.90
#Mann= 3 , 0 , 0
       0     0.1       0     652   0.045       0     667     0.1       0
Bank Sta=     652,     667
Exp/Cntr=0.3,0.1

Type RM Length L Ch R = 1 ,6464,483.485,470.302,457.066
XS GIS Cut Line= 3
     1674015.423      293665.944     1673912.445      293176.013
     1673762.366      292696.604
#Sta/Elev= 30
       0 1133.76    38.0 1124.86    74.4 1113.55    86.3 1110.63    98.7 1108.98
   110.8 1106.44   159.3 1092.48   232.1 1069.70   246.7 1066.05   256.4 1064.94
   268.5 1064.35   402.0 1059.19   493.1 1054.29   499.0 1054.13   508.1 1056.33
   511.4 1057.07   536.3 1069.55   556.0 1078.16   592.3 1093.64   610.9 1101.05
   747.8 1147.37   762.8 1152.27   785.1 1158.64   810.9 1167.05   884.6 1194.43
   934.4 1215.30   946.8 1219.47   971.7 1225.53   984.2 1227.41  1003.0 1228.45
#Mann= 3 , 0 , 0
       0     0.1       0   493.1   0.045       0   508.1     0.1       0
Bank Sta=   493.1,   508.1
Exp/Cntr=0.3,0.1

Type RM Length L Ch R = 1 ,5993.7,445.139,449.95,456.068
XS GIS Cut Line= 3
     1674752.035      293404.392     1674256.673      292947.901
     1673892.910      292591.741
#Sta/Elev= 30
       0 1135.40    40.7 1125.62    72.5 1116.67   114.5 1110.41   202.2 1095.43
   240.5 1090.21   274.1 1086.42   299.1 1077.44   307.7 1076.08   417.0 1067.47
   544.9 1061.81   669.9 1053.96   670.4 1053.94   677.4 1053.98   684.9 1055.45
   718.6 1070.17   735.6 1076.61   752.6 1082.19   778.2 1089.60   811.8 1100.95
   878.9 1125.04   954.5 1154.89   990.2 1171.28  1046.8 1200.36  1088.8 1219.88
  1102.3 1225.48  1114.0 1229.80  1130.8 1234.68  1152.2 1239.06  1182.7 1244.28
#Mann= 3 , 0 , 0
       0     0.1       0   669.9   0.045       0   684.9     0.1       0
Bank Sta=   669.9,   684.9
Exp/Cntr=0.3,0.1

Type RM Length L Ch R = 1 ,5543.8,320.639,326.783,330.776
XS GIS Cut Line= 3
     1674932.264      293190.787     1674551.037      292638.791
     1674313.387      292187.999
#Sta/Elev= 30
       0 1108.22    30.5 1102.55    59.3 1092.73    73.7 1091.83   102.6 1100.42
   131.5 1099.61   174.7 1095.54   232.5 1084.83   275.7 1082.66   328.1 1074.20
   373.9 1065.15   390.7 1063.28   434.5 1060.75   506.6 1060.70   655.6 1049.79
   656.1 1049.80   664.1 1049.98   671.1 1052.26   679.1 1054.64   692.6 1061.15
   706.0 1066.09   786.5 1089.98   867.0 1122.29   920.7 1133.22   934.1 1136.87
   947.6 1142.68  1041.5 1189.48  1068.9 1201.65  1148.9 1221.49  1180.4 1227.72
#Mann= 3 , 0 , 0
       0     0.1       0   656.1   0.045       0   671.1     0.1       0
Bank Sta=   656.1,   671.1
Exp/Cntr=0.3,0.1

Type RM Length L Ch R = 1 ,5217,355.899,352.965,354.02
XS GIS Cut Line= 3
     1675009.842      292992.470     1674850.552      292518.081
     1674696.408      292093.834
#Sta/Elev= 30
       0 1130.17    71.7 1121.29    83.4 1118.96    92.8 1116.33   105.3 1111.92
   155.4 1093.27   165.4 1090.59   184.2 1087.60   193.0 1085.05   268.1 1058.94
   280.6 1055.43   293.1 1054.03   344.5 1052.15   504.1 1049.04   506.1 1049.02
   519.2 1050.42   521.5 1051.09   531.4 1055.63   544.0 1060.75   660.4 1089.91
   669.7 1092.88   737.5 1117.48   762.4 1125.11   784.0 1129.01   818.0 1133.68
   830.4 1135.78   847.2 1137.67   897.7 1141.08   919.9 1141.73   951.8 1141.86
#Mann= 3 , 0 , 0
       0     0.1       0   504.1   0.045       0   519.2     0.1       0
Bank Sta=   504.1,   519.2
Exp/Cntr=0.3,0.1

Type RM Length L Ch R = 1 ,4864,399.066,400,396.106
XS GIS Cut Line= 3
     1675360.307      292797.351     1675136.551      292348.881
     1674984.643      291868.219
#Sta/Elev= 30
       0 1129.31    39.4 1116.98    92.5 1096.76   105.8 1092.57   145.6 1085.82
   185.4 1074.74   236.6 1063.56   265.0 1051.29   278.3 1050.58   411.0 1050.10
   490.6 1048.17   493.7 1048.18   503.7 1048.33   508.7 1049.27   528.6 1053.81
   540.1 1055.71   565.9 1056.24   603.3 1058.94   665.5 1065.29   678.0 1067.49
   752.7 1087.70   765.2 1091.73   795.5 1105.02   814.4 1114.25   827.4 1118.82
   852.2 1124.81   877.2 1131.91   889.7 1134.56   976.8 1147.49  1005.3 1153.70
#Mann= 3 , 0 , 0
       0     0.1       0   493.7   0.045       0   508.7     0.1       0
Bank Sta=   493.7,   508.7
Exp/Cntr=0.3,0.1

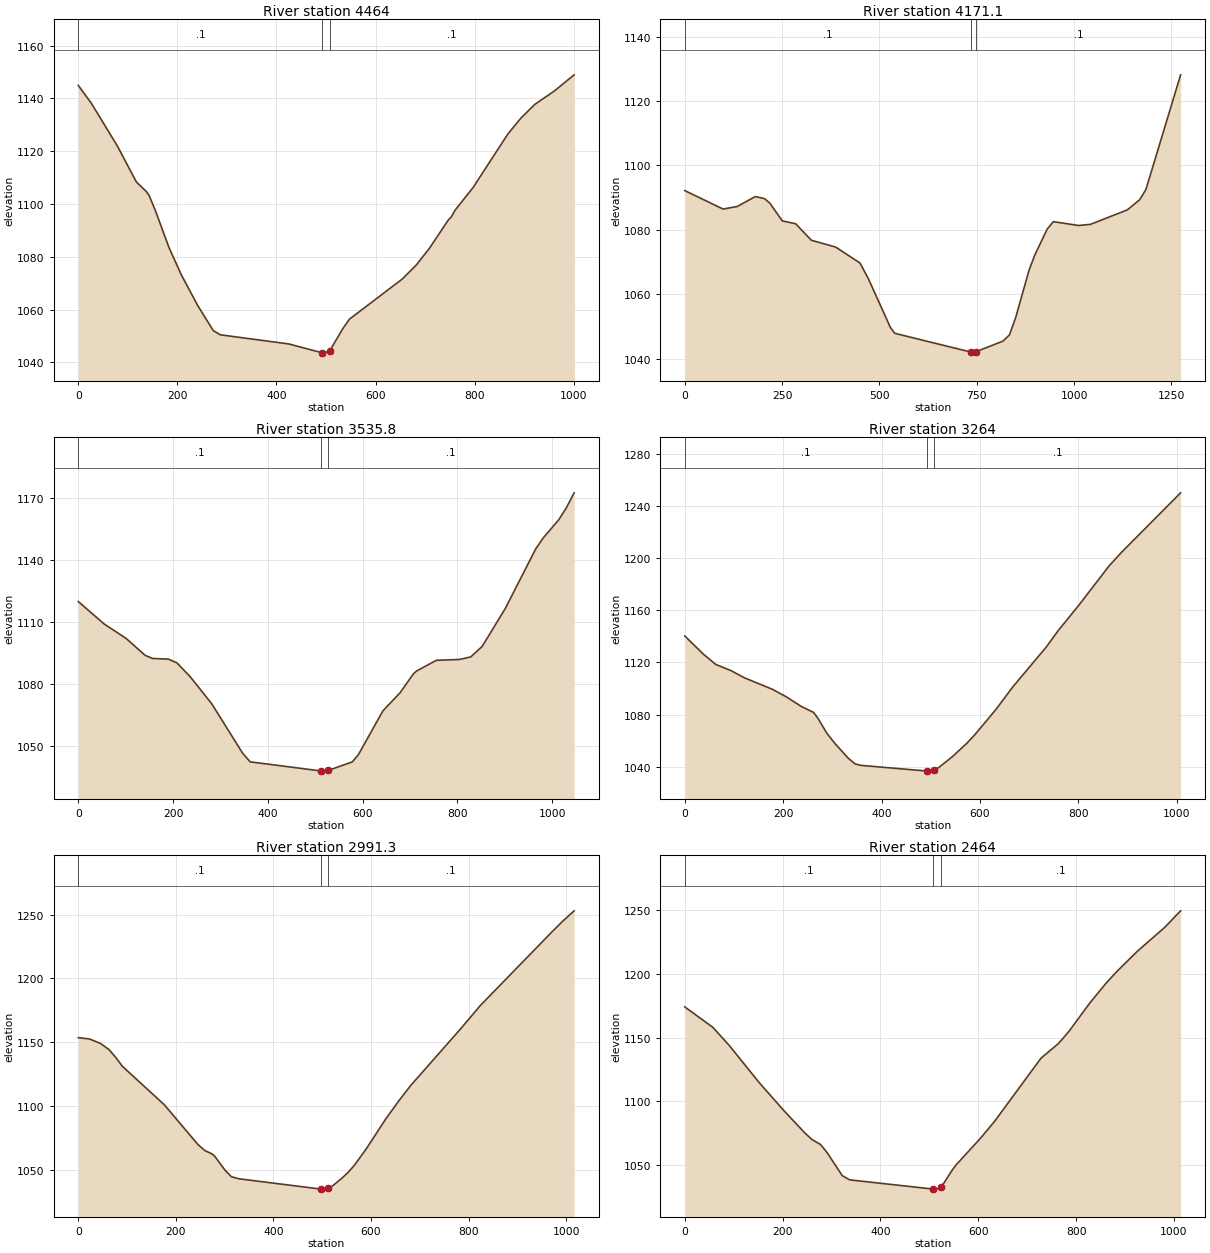
Type RM Length L Ch R = 1 ,4464,296.734,292.859,284.24
XS GIS Cut Line= 3
     1675711.084      292655.345     1675506.594      292198.670
     1675279.351      291751.895
#Sta/Elev= 30
       0 1144.88    26.2 1138.15    78.2 1122.15   117.2 1108.32   137.6 1104.65
   143.2 1103.10   155.6 1097.48   183.0 1083.50   208.3 1073.01   241.1 1061.51
   272.4 1052.04   286.3 1050.44   425.1 1046.96   492.9 1043.59   497.0 1043.49
   507.9 1044.48   534.3 1052.85   547.6 1056.38   654.2 1071.58   682.5 1076.91
   709.0 1083.22   747.4 1094.03   753.1 1095.07   760.7 1097.64   797.2 1106.26
   867.3 1126.50   893.9 1132.56   921.4 1137.67   960.5 1142.69  1001.1 1148.90
#Mann= 3 , 0 , 0
       0     0.1       0   492.9   0.045       0   507.9     0.1       0
Bank Sta=   492.9,   507.9
Exp/Cntr=0.3,0.1

Type RM Length L Ch R = 1 ,4171.1,633.317,635.357,633.74
XS GIS Cut Line= 4
     1676124.895      292683.474     1675964.154      292367.890
     1675742.832      292050.574     1675343.900      291697.773
#Sta/Elev= 30
       0 1092.18    98.3 1086.45   134.8 1087.25   181.3 1090.34   204.9 1089.67
   218.3 1088.31   250.5 1082.77   284.9 1081.88   324.9 1076.77   387.7 1074.63
   450.0 1069.69   470.7 1065.02   528.3 1049.64   539.4 1047.85     734 1042.06
   741.4 1041.70     749 1042.18   817.1 1045.43   834.0 1047.36   849.9 1052.74
   884.4 1067.50   899.1 1072.19   930.8 1080.21   946.7 1082.54  1011.2 1081.34
  1041.8 1081.69  1136.6 1086.18  1168.6 1089.37  1184.4 1092.50  1273.6 1128.14
#Mann= 3 , 0 , 0
       0     0.1       0     734   0.045       0     749     0.1       0
Bank Sta=     734,     749
Exp/Cntr=0.3,0.1

Type RM Length L Ch R = 1 ,3535.8,268.172,271.784,276.968
XS GIS Cut Line= 3
     1676498.093      292191.181     1676153.812      291800.805
     1675766.558      291444.715
#Sta/Elev= 30
       0 1119.94    54.7 1109.04   100.3 1102.20   141.1 1093.89   157.0 1092.38
   190.1 1092.08   208.0 1090.29   236.1 1083.58   281.8 1070.41   346.9 1046.52
   362.8 1042.37   512.2 1037.96   517.4 1037.88   527.2 1038.20   578.4 1042.36
   591.3 1045.89   642.9 1067.04   679.0 1075.77   707.4 1084.98   714.1 1086.34
   755.8 1091.51   804.2 1091.90   828.3 1093.14   852.6 1098.27   901.0 1116.48
   965.5 1145.41   981.6 1150.80  1013.9 1159.45  1029.8 1165.16  1046.6 1172.54
#Mann= 3 , 0 , 0
       0     0.1       0   512.2   0.045       0   527.2     0.1       0
Bank Sta=   512.2,   527.2
Exp/Cntr=0.3,0.1

Type RM Length L Ch R = 1 ,3264,272.928,272.742,275.133
XS GIS Cut Line= 3
     1676619.565      292069.686     1676354.134      291646.643
     1676068.046      291226.031
#Sta/Elev= 30
       0 1140.22    37.6 1126.34    63.0 1118.39    93.7 1113.73   121.7 1108.09
   177.8 1099.42   205.8 1093.71   236.9 1086.22   261.9 1081.62   271.3 1076.80
   288.5 1065.87   303.9 1058.43   331.9 1046.71   346.0 1042.25   357.4 1041.10
   491.9 1036.74   495.2 1036.66   506.9 1037.63   514.5 1038.92   543.2 1047.50
   572.0 1057.50   589.3 1064.43   632.0 1083.63   666.2 1100.92   734.6 1131.63
   758.6 1144.07   801.7 1164.08   862.7 1193.97   887.8 1204.32  1008.0 1249.90
#Mann= 3 , 0 , 0
       0     0.1       0   491.9   0.045       0   506.9     0.1       0
Bank Sta=   491.9,   506.9
Exp/Cntr=0.3,0.1

Type RM Length L Ch R = 1 ,2991.3,532.168,527.258,515.864
XS GIS Cut Line= 3
     1676847.835      291924.364     1676572.056      291489.305
     1676369.606      291030.612
#Sta/Elev= 30
       0 1153.53    23.2 1152.45    45.4 1148.99    62.5 1144.33    76.5 1138.16
    90.2 1131.11   176.3 1100.93   245.2 1069.79   259.3 1065.03   273.3 1062.58
   279.5 1060.66   301.4 1049.35   313.9 1044.51   329.5 1042.89   496.6 1034.87
   503.2 1034.80   511.6 1035.44   520.7 1037.19   539.2 1043.01   551.4 1047.28
   565.7 1053.36   590.4 1066.44   630.8 1090.14   656.8 1103.88   681.2 1115.95
   785.0 1161.01   824.0 1178.66   970.8 1236.37   992.7 1244.68  1016.5 1252.94
#Mann= 3 , 0 , 0
       0     0.1       0   496.6   0.045       0   511.6     0.1       0
Bank Sta=   496.6,   511.6
Exp/Cntr=0.3,0.1

Type RM Length L Ch R = 1 ,2464,405.243,400,399.575
XS GIS Cut Line= 3
     1677285.429      291442.871     1676887.729      291114.499
     1676463.490      290854.045
#Sta/Elev= 30
       0 1174.10    57.3 1158.06    91.2 1143.66   152.5 1114.39   203.0 1092.42
   244.9 1075.26   259.7 1069.93   277.6 1065.94   291.0 1059.53   321.8 1041.53
   337.2 1038.16   508.2 1030.90   512.7 1030.88   521.0 1031.87   523.2 1032.83
   529.9 1035.75   547.1 1046.12   555.8 1050.39   605.0 1071.11   633.5 1084.27
   728.4 1133.91   762.9 1145.00   771.6 1148.68   786.1 1155.27   827.9 1177.14
   861.4 1192.84   883.6 1202.08   925.4 1217.93   981.1 1236.62  1013.6 1249.62
#Mann= 3 , 0 , 0
       0     0.1       0   508.2   0.045       0   523.2     0.1       0
Bank Sta=   508.2,   523.2
Exp/Cntr=0.3,0.1

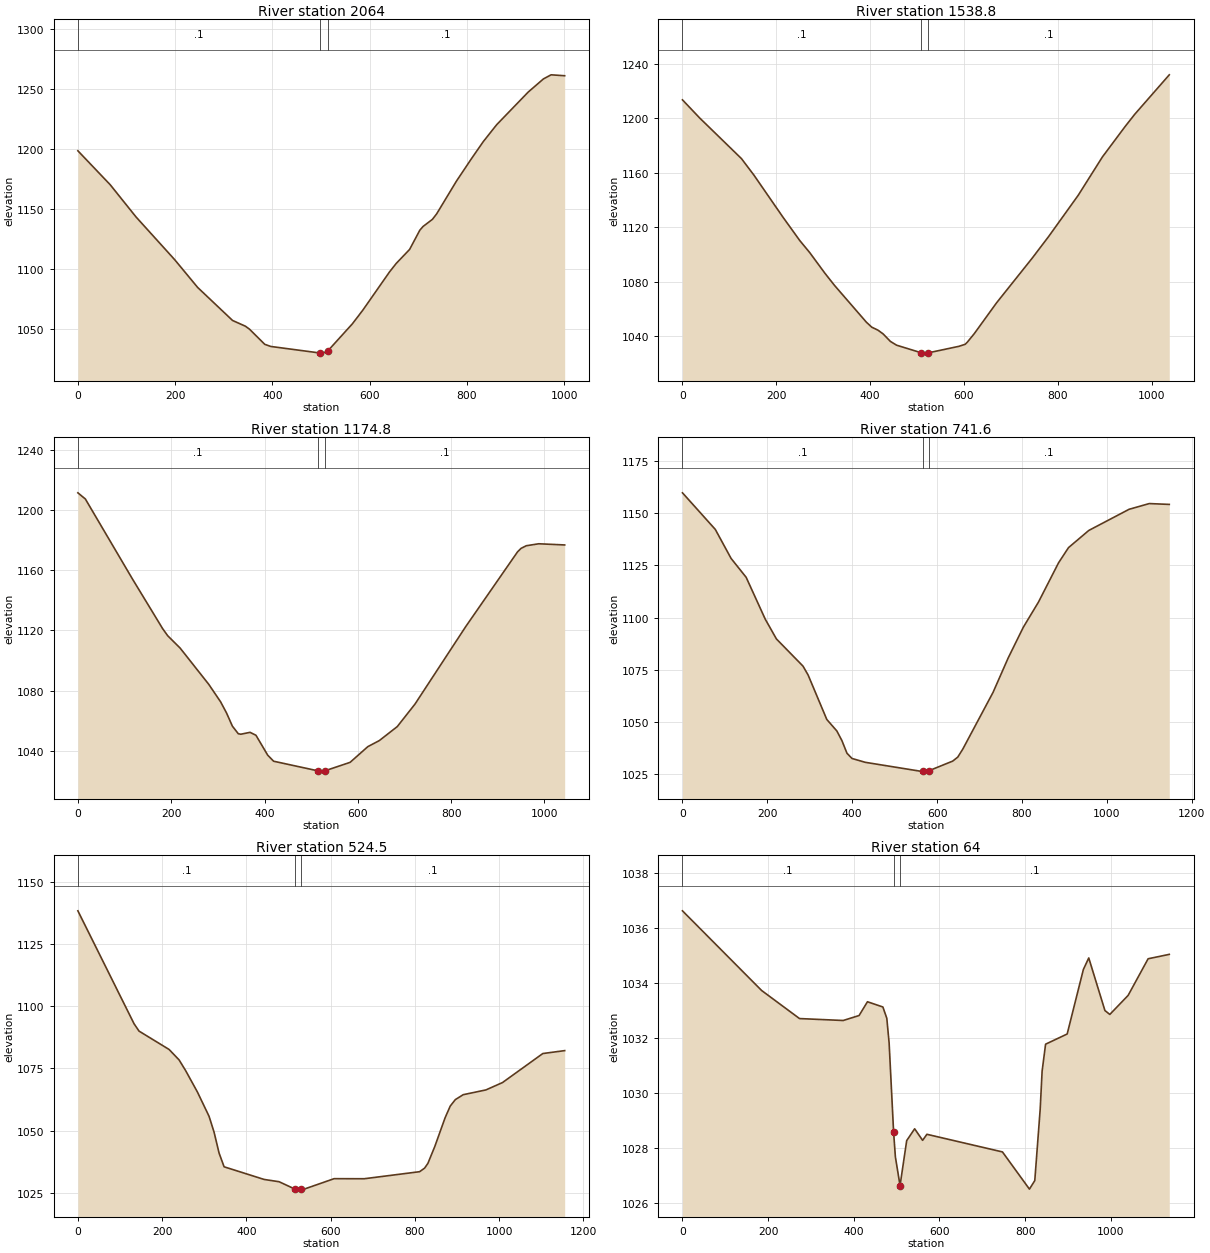
Type RM Length L Ch R = 1 ,2064,492.013,525.238,496.466
XS GIS Cut Line= 3
     1677560.056      291061.407     1677106.053      290837.806
     1676679.201      290587.124
#Sta/Elev= 30
       0 1198.29    66.6 1169.97   119.6 1143.18   199.0 1107.63   246.4 1084.43
   318.1 1056.96   344.6 1052.16   352.9 1049.71   384.3 1037.09   396.6 1035.31
   498.6 1029.82   503.4 1029.75   513.6 1031.42   564.4 1054.11   585.9 1065.50
   640.9 1097.39   654.7 1104.48   682.2 1116.13   703.2 1132.14   709.8 1135.23
   729.2 1141.22   737.9 1145.80   778.6 1173.08   809.1 1191.55   833.7 1205.93
   861.2 1220.00   926.3 1247.29   957.6 1258.22   973.2 1261.57  1001.1 1260.81
#Mann= 3 , 0 , 0
       0     0.1       0   498.6   0.045       0   513.6     0.1       0
Bank Sta=   498.6,   513.6
Exp/Cntr=0.3,0.1

Type RM Length L Ch R = 1 ,1538.8,364.957,363.918,361.643
XS GIS Cut Line= 3
     1677803.046      290751.684     1677324.279      290516.714
     1676876.832      290284.603
#Sta/Elev= 30
       0 1213.48    37.0 1200.06   125.7 1170.35   152.1 1158.31   214.4 1127.25
   249.9 1110.25   271.1 1101.41   303.2 1086.37   324.0 1077.29   391.9 1050.29
   403.4 1046.63   416.6 1044.44   427.4 1041.75   443.1 1036.19   456.3 1033.40
   508.4 1027.89   516.1 1027.58   523.4 1027.76   589.2 1032.58   602.5 1034.07
   607.6 1035.85   621.9 1041.91   669.4 1064.53   745.2 1097.25   780.4 1113.21
   843.3 1143.41   894.9 1171.58   942.8 1193.68   963.7 1202.85  1037.4 1231.85
#Mann= 3 , 0 , 0
       0     0.1       0   508.4   0.045       0   523.4     0.1       0
Bank Sta=   508.4,   523.4
Exp/Cntr=0.3,0.1

Type RM Length L Ch R = 1 ,1174.8,411.29,433.21,422.974
XS GIS Cut Line= 3
     1677895.246      290391.476     1677388.957      290210.336
     1676913.837      290037.299
#Sta/Elev= 30
       0 1211.40    16.0 1207.32   116.8 1154.28   182.0 1121.06   192.5 1116.52
   219.2 1108.30   280.8 1084.13   306.0 1072.58   318.6 1065.25   331.2 1056.47
   343.8 1051.45   349.2 1051.11   369.0 1052.36   381.7 1050.42   406.9 1037.21
   419.5 1033.19   515.4 1026.74   520.4 1026.61   530.4 1026.91   583.5 1032.44
   621.4 1042.85   646.1 1046.89   684.6 1056.19   722.5 1071.10   831.3 1122.57
   942.5 1172.26   949.9 1174.51   961.0 1176.26   987.8 1177.57  1043.4 1176.79
#Mann= 3 , 0 , 0
       0     0.1       0   515.4   0.045       0   530.4     0.1       0
Bank Sta=   515.4,   530.4
Exp/Cntr=0.3,0.1

Type RM Length L Ch R = 1 ,741.6,216.922,217.131,218.175
XS GIS Cut Line= 3
     1677947.216      289971.129     1677375.527      289966.286
     1676800.202      289976.637
#Sta/Elev= 30
       0 1159.64    77.4 1142.13   114.5 1128.28   150.1 1119.21   195.1 1099.19
   221.4 1089.74   284.0 1076.75   296.0 1072.52   340.1 1051.23   363.8 1045.72
   375.7 1041.12   387.6 1035.08   399.5 1032.57   430.6 1030.74   559.4 1026.52
   565.7 1026.52   580.7 1026.70   636.9 1031.33   648.8 1033.25   660.7 1037.11
   731.9 1064.21   767.5 1080.65   803.2 1095.36   838.8 1107.35   886.3 1126.20
   909.7 1133.44   957.5 1141.65  1052.5 1151.77  1100.0 1154.50  1147.1 1154.10
#Mann= 3 , 0 , 0
       0     0.1       0   565.7   0.045       0   580.7     0.1       0
Bank Sta=   565.7,   580.7
Exp/Cntr=0.3,0.1

Type RM Length L Ch R = 1 ,524.5,468.529,460.503,452.389
XS GIS Cut Line= 4
     1677906.676      289758.408     1677378.817      289750.627
     1677110.718      289742.399     1676761.261      289826.501
#Sta/Elev= 30
       0 1138.29   133.3 1092.94   145.2 1089.97   216.5 1082.60   240.2 1078.41
   255.7 1074.13   283.6 1065.56   311.4 1055.75   323.3 1049.38   335.2 1040.97
   347.1 1035.46   442.1 1030.38   477.7 1029.46   515.3 1026.50   530.3 1026.51
   537.1 1026.49   608.3 1030.69   679.6 1030.66   811.2 1033.49   822.9 1034.90
   830.8 1036.80   847.3 1043.62   871.7 1055.14   883.9 1059.84   896.1 1062.46
   914.8 1064.43   968.6 1066.34  1008.0 1069.30  1103.7 1080.96  1155.6 1082.13
#Mann= 3 , 0 , 0
       0     0.1       0   515.3   0.045       0   530.3     0.1       0
Bank Sta=   515.3,   530.3
Exp/Cntr=0.3,0.1

Type RM Length L Ch R = 1 ,64,63.858,64.002,63.957
XS GIS Cut Line= 3
     1677775.570      289160.816     1677305.253      289332.033
     1676705.167      289544.782
#Sta/Elev= 30
       0 1036.61   184.7 1033.72   273.3 1032.70   375.2 1032.63   412.3 1032.81
   431.9 1033.31   467.9 1033.12   477.1 1032.71   482.5 1031.81     493 1028.57
   497.1 1027.68     508 1026.64   523.5 1028.27   542.1 1028.70   560.7 1028.28
   570.7 1028.50   747.1 1027.86   810.1 1026.51   822.6 1026.82   835.2 1029.41
   839.7 1030.79   847.8 1031.77   898.2 1032.14   936.0 1034.48   948.6 1034.90
   986.4 1032.99   997.8 1032.85  1040.5 1033.54  1087.2 1034.87  1136.6 1035.03
#Mann= 3 , 0 , 0
       0     0.1       0     493   0.045       0     508     0.1       0
Bank Sta=     493,     508
Exp/Cntr=0.3,0.1